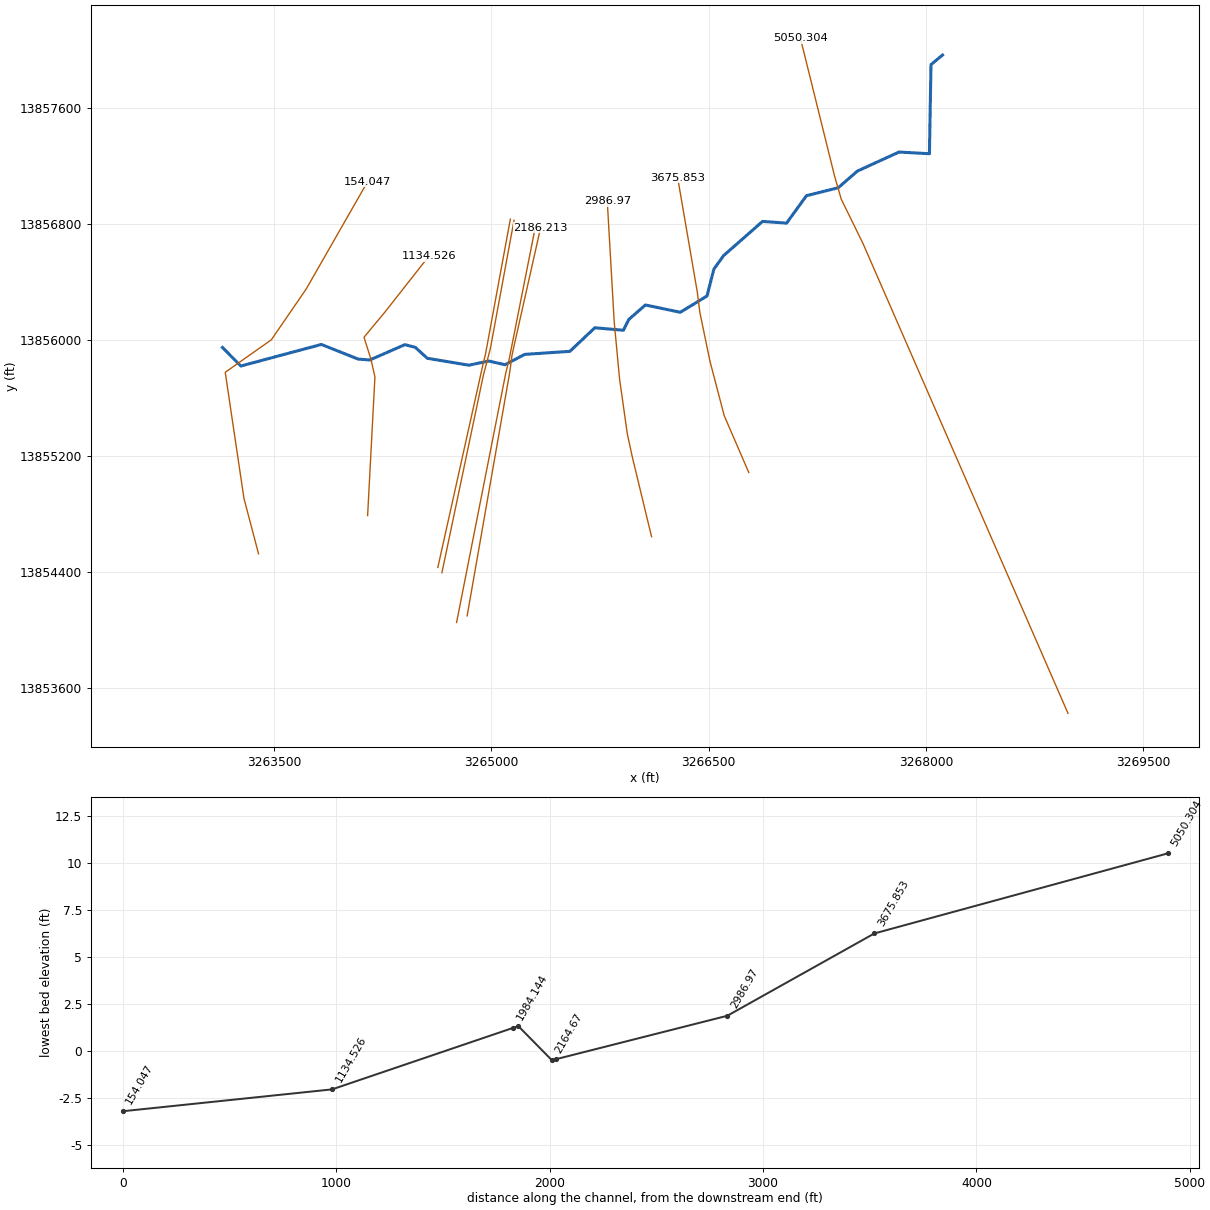
--- Q1130000.prj (project) ---

Proj Title=Q113-00-00
Current Plan=p01
Default Exp/Contr=.3,.1
English Units
Geom File=g04
Flow File=f01
Flow File=f04
Plan File=p01
Plan File=p03
Y Axis Title=Elevation
X Axis Title(PF)=Main Channel Distance
X Axis Title(XS)=Station
BEGIN DESCRIPTION:
Cedar Bayou Watershed
HCFCD UNIT NO. Q113-00-00
Horsepen Bayou
(Flood Hazard) Model
10, 2, 1, 0.2% Event
Filename horsepen.prj
Prepared by:  FTN Associates Ltd.   DATE:  May 2003
Reviewed by:     DATE:
STATUS (FINAL RAS)
Normal Depth Slope calculated between RS 3011.819 and RS 154.047 with inverts 1.88 and -3.19 respectively. Distance between cross sections is 2857.772. Normal Depth Slope Calculated to be 0.001774.
Flow files developed from information given at confluence w/ Cedar Bayou.  Manning's n values used based on that used in effective models for other streams within Cedar Bayou watershed, and land use analysis based on aerial photos and on photos of overbanks at structures along this study stream.
END DESCRIPTION:
DSS Export Rating Curves= 0
DSS Export Rating Curve Sorted= 0
DSS Export Volume Flow Curves= 0
DXF OffsetX= 0
DXF OffsetY= 0
DXF ScaleX= 1
DXF ScaleY= 10

--- Q1130000.p01 (plan) ---

Plan Title=Floodway
Version=Version 3.0.1  Mar 2001
Short Identifier=Floodway0607
Geom File=g04
Flow File=f01
Subcritical Flow
K Sum by GR= 0
Std Step Tol= 0.01
Critical Tol= 0.01
Num of Std Step Trials= 20
Max Error Tol= 0.3
Flow Tol Ratio= 0.001
Split Flow NTrial= 30
Split Flow Tol= 0.02
Split Flow Ratio= 0.02
Log Output Level= 0
Friction Slope Method= 1
Unsteady Friction Slope Method= 2
Parabolic Critical Depth
Global Vel Dist= 0 , 0 , 0
Global Log Level= 0
CheckData=True
Encroach Param=-1 ,0,0, 2
Encroach River=Q113-00-00
Encroach Reach=Q113-00-00
Encroach Node=5050.304
       1  889.94 1017.95
Encroach Node=3675.853
       1 1225.51 1255.43
Encroach Node=2986.97
       1 1429.33 1488.01
Encroach Node=2186.213
       1 1767.39 1806.74
Encroach Node=2164.67
       1 1808.48 1840.77
Encroach Node=2086.12
       1 1796.31  1850.2
Encroach Node=2007.57
       1 1796.31  1850.2
Encroach Node=1984.144
       1 1441.56 1495.45
Encroach Node=1134.526
       1 1052.65 1114.68
Encroach Node=154.047
       1    1205    1460
Computation Interval=1HOUR
Output Interval=1HOUR
Run HTab= 0
Run UNet= 0
Run PostProcess= 0
UNET Theta= 1
UNET ZTol= 0.02
UNET ZSATol= 0.1
UNET MxIter= 20
UNET MaxInSteps= 20
UNET DtIC= 0
UNET DtMin= 0
UNET MaxCRTS= 20
UNET WFStab= 2
UNET SFStab= 1
UNET WFX= 1
UNET SFX= 1
UNET Convert EG Bridges=-1
UNET Use Existing IB Tables=-1
Instantaneous Interval=1HOUR
Write IC File= 0
Write Velocity= 0
Write Detailed= 0

--- Q1130000.p03 (plan) ---

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Plan Title=FEMA Effective June 2007
Short Identifier=FEMAeff0607
Geom File=g04
Flow File=f04
Encroach Param=-1 ,0,0, 0

--- Q1130000.f01 (steady flow) ---

Flow Title=Floodway
Version=Version 3.0.1  Mar 2001
Number of Profiles= 2
Profile Names=1PCT_100yr,1PCT_Floodway
River Rch & RM=Q113-00-00,Q113-00-00      ,5050.304
     995     995
River Rch & RM=Q113-00-00,Q113-00-00      ,3675.853
    1028    1028
River Rch & RM=Q113-00-00,Q113-00-00      ,2986.97
    1078    1078
River Rch & RM=Q113-00-00,Q113-00-00      ,1984.144
    1122    1122
River Rch & RM=Q113-00-00,Q113-00-00      ,1134.526
    1175    1175
Boundary for River Rch & Prof#=Q113-00-00,Q113-00-00      , 1
Up Type= 0
Dn Type= 3
Dn Slope=.001774
Boundary for River Rch & Prof#=Q113-00-00,Q113-00-00      , 2
Up Type= 0
Dn Type= 3
Dn Slope=.001774
DSS Import GetInterval= 0
DSS Import GetPeak= 0
DSS Import FillOption= 0

--- Q1130000.f04 (steady flow) ---

Flow Title=FEMA Effective June 2007
Version=Version 3.0.1  Mar 2001
Number of Profiles= 4
Profile Names=10PCT_10yr,2PCT_50yr,1PCT_100yr,0.2PCT_500yr
River Rch & RM=Horsepen Bayou,Horsepen_0002   ,5050.304
     411     775     995    1706
River Rch & RM=Horsepen Bayou,Horsepen_0002   ,3675.853
     425     801    1028    1763
River Rch & RM=Horsepen Bayou,Horsepen_0002   ,2986.97
     445     839    1078    1848
River Rch & RM=Horsepen Bayou,Horsepen_0002   ,1984.144
     463     873    1122    1923
River Rch & RM=Horsepen Bayou,Horsepen_0002   ,1134.526
     485     915    1175    2014
River Rch & RM=Q113-00-00,Q113-00-00      ,5050.304
     411     775     995    1706
River Rch & RM=Q113-00-00,Q113-00-00      ,3675.853
     425     801    1028    1763
River Rch & RM=Q113-00-00,Q113-00-00      ,2986.97
     445     839    1078    1848
River Rch & RM=Q113-00-00,Q113-00-00      ,1984.144
     463     873    1122    1923
River Rch & RM=Q113-00-00,Q113-00-00      ,1134.526
     485     915    1175    2014
Boundary for River Rch & Prof#=Q113-00-00,Q113-00-00      , 1
Up Type= 0
Dn Type= 3
Dn Slope=.001774
DSS Import GetInterval= 0
DSS Import GetPeak= 0
DSS Import FillOption= 0

--- Q1130000.g04 (geometry) ---

Geom Title=Q113-00-00 June 2007
Version=Version 3.0.1  Mar 2001

River Reach=Q113-00-00      ,Q113-00-00
Reach XY= 30
      3268113.83     13857968.63     3268034.081     13857902.17
     3268023.322      13857287.8     3267813.464     13857299.29
     3267526.488     13857168.05      3267393.89     13857052.75
     3267174.814     13856997.98     3267037.859     13856808.88
     3266872.143      13856820.7     3266604.063     13856585.77
     3266536.322     13856492.08      3266488.76     13856306.16
     3266304.275     13856193.74      3266063.58     13856244.18
     3265949.791     13856144.82      3265911.84     13856069.61
     3265714.788     13856087.08     3265542.671     13855924.23
     3265231.111     13855903.26     3265095.095      13855831.9
     3264982.592     13855857.47      3264845.62     13855828.64
      3264558.41     13855876.51      3264476.35     13855951.73
     3264404.548     13855970.53     3264161.787     13855864.54
     3264081.807     13855870.89      3263828.14     13855971.78
     3263272.252     13855823.05     3263145.386     13855951.19

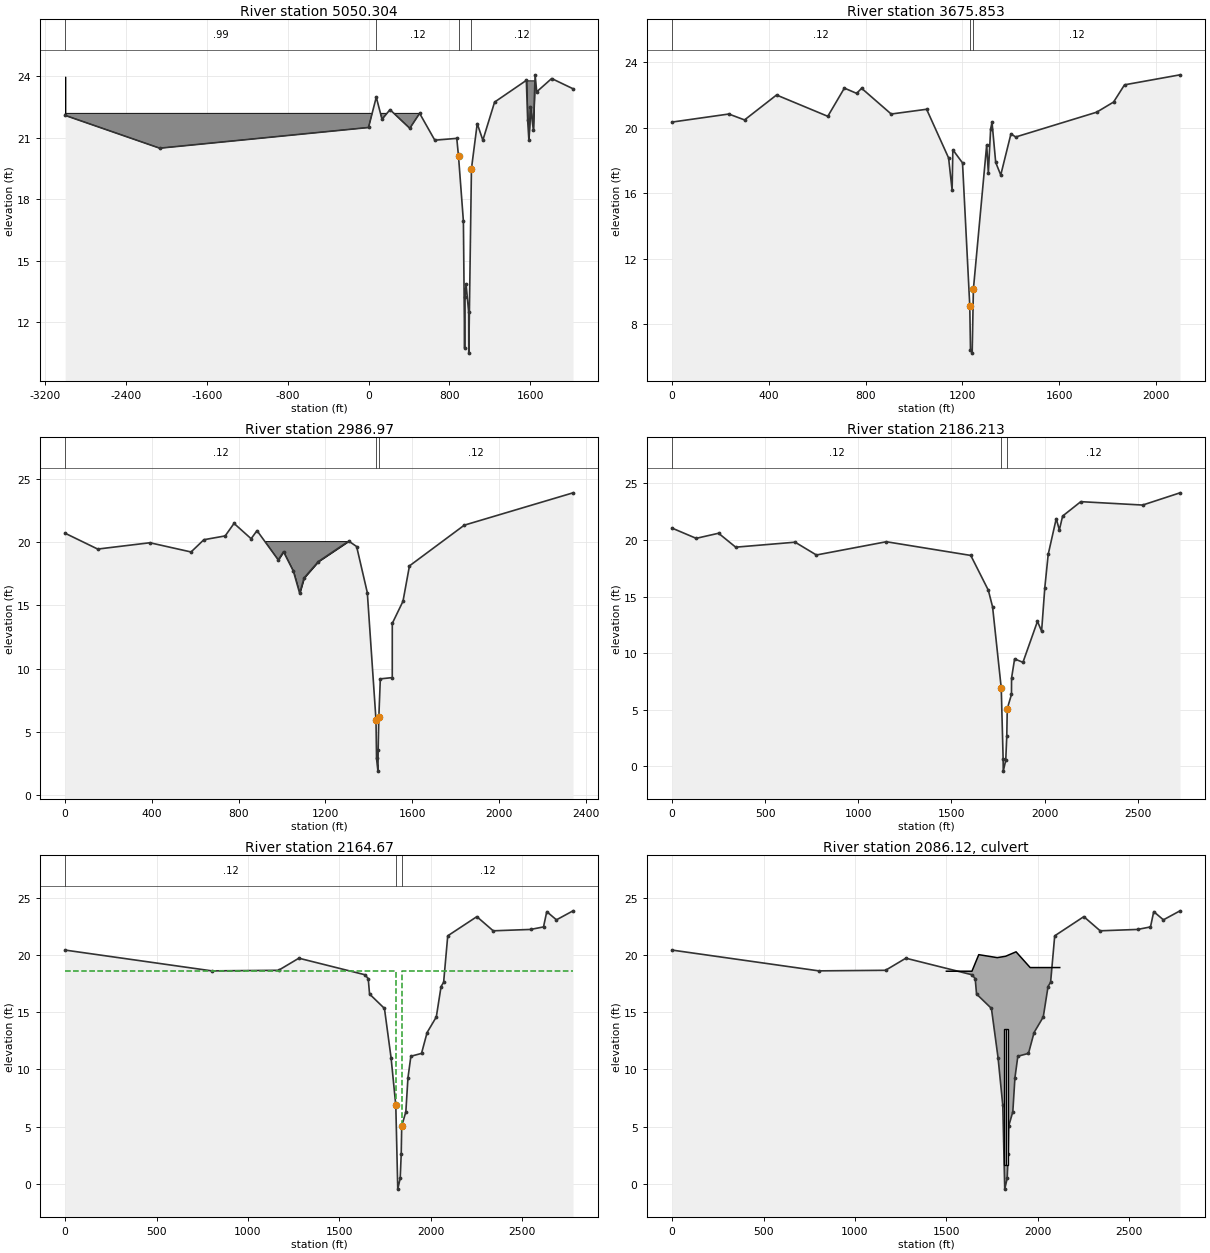
Type RM Length L Ch R = 1 ,5050.304,1335.35,1374.45,1311.14
BEGIN DESCRIPTION:
433v1
Bank Station offset =      4008
First two points were added to cross section data from LIDAR information on far LOB, but section was blocked on far LOB based on high ground elevations of TIN.  Block was added on ROB to prevent storage in st. or lateral ditch.
END DESCRIPTION:
XS GIS Cut Line= 6
 3268979.615909713853426.3835376     3267565.815    13856666.339
     3267414.832    13856974.345     3267394.083    13857046.105
     3267368.957    13857132.996     3267133.426    13858083.862
#Sta/Elev= 30
   -3000    22.1   -2065    20.5       0   21.51   76.68   22.99  133.53   21.91
  212.36   22.38   408.2   21.47  505.41    22.2  655.63   20.89  872.86   20.98
  889.94   20.11  938.36   16.94   950.4   10.75  954.74   13.24  964.77   13.87
  990.79   12.49  991.71    10.5 1017.95    19.5 1075.16    21.7 1130.74   20.89
 1246.92   22.75 1560.85   23.81 1573.87   21.87  1585.9   20.91 1601.35   22.51
 1629.92   21.41 1647.71   24.08 1663.32   23.25 1811.15    23.9 2022.76    23.4
#Mann= 4 ,-1 , 0
   -3000     .99       0   76.68     .12       0  889.94     .08       0
 1017.95     .12       0
#Block Obstruct= 3 ,-1
 1560.85 1647.71   23.81   -3000   -2999      24   -2999  505.41    22.2
Bank Sta=889.94,1017.95
XS Rating Curve= 0
Exp/Cntr=.3,.1

Type RM Length L Ch R = 1 ,3675.853,632.41,688.88,673.68
BEGIN DESCRIPTION:
433v2
Bank Station offset =      3759
END DESCRIPTION:
XS GIS Cut Line= 6
     3266776.816    13855088.341     3266607.426    13855480.612
     3266509.359    13855855.052     3266439.036    13856194.473
     3266421.833    13856333.053     3266286.478    13857121.016
#Sta/Elev= 30
       0   20.34  234.25   20.83  299.35   20.47  431.63   21.99  643.59   20.69
  712.13   22.41  762.88   22.09  783.42    22.4  905.74   20.83 1052.26   21.12
 1143.16   18.15 1157.69   16.18 1160.67   18.65 1200.67   17.85 1230.67    9.15
 1233.67    6.45 1240.67    6.25 1245.67   10.15 1300.67   18.95 1307.48   17.23
 1316.98   19.92  1322.7   20.32 1337.92   17.88 1358.77   17.11 1400.95   19.62
 1420.65   19.43 1755.15   20.94 1825.39   21.56 1870.61   22.61 2100.13   23.22
#Mann= 3 ,-1 , 0
       0     .12       0 1230.67     .08       0 1245.67     .12       0
Bank Sta=1230.67,1245.67
XS Rating Curve= 0
Exp/Cntr=.3,.1

Type RM Length L Ch R = 1 ,2986.97 ,788.16,800.76,779.8
BEGIN DESCRIPTION:
433v3
Bank Station offset =      3558
Adjusted Manning's "n" values.
Blocked ravine in LOB that is part of side channel.
END DESCRIPTION:
XS GIS Cut Line= 6
     3266106.159    13854645.397     3265974.444    13855190.866
     3265938.783    13855355.798     3265885.292    13855734.696
     3265848.398    13856128.528     3265800.597    13856960.542
#Sta/Elev= 30
       0    20.7  149.92   19.45  390.72   19.95  580.35   19.22  639.42   20.19
  737.61   20.49  778.47   21.48  857.25   20.27   884.4   20.91  982.33   18.59
 1006.56   19.24 1052.13    17.7  1081.1   15.95 1101.49   17.17 1167.02   18.46
 1307.47   20.08 1343.71   19.65 1392.99      16 1432.99    5.93 1435.49    2.88
 1441.99    1.88 1442.99    3.58 1445.99    6.13 1452.99    9.18 1507.99    9.28
  1508.1   13.57  1557.4   15.32 1587.29   18.12 1839.94   21.34 2341.49    23.9
#Mann= 3 , 0 , 0
       0     .12       0 1432.99     .08       0 1445.99     .12       0
#Block Obstruct= 1 ,-1
     900 1307.47   20.08
Bank Sta=1432.99,1445.99
XS Rating Curve= 0
Exp/Cntr=.3,.1

Type RM Length L Ch R = 1 ,2186.213,25.92,21.54,18.28
BEGIN DESCRIPTION:
XS 4/4.  Copy of 433s1ufix.  Adjusted elevations to match slope between XS 3/4 at 2220.877 and RS 3011.819
END DESCRIPTION:
XS GIS Cut Line= 6
     3264833.824    13854099.339     3265122.734     13855751.01
     3265133.102    13855818.612     3265142.641    13855892.849
     3265152.044     13855937.75      3265340.99    13856778.367
#Sta/Elev= 30
       0   21.04  128.99   20.14   249.2   20.59  341.27   19.36  660.35    19.8
   774.6   18.67 1150.32   19.84 1603.68   18.63 1697.92   15.56 1720.77   14.09
 1767.39    6.91 1777.47     .64 1778.12    -.42  1791.5     .53 1797.07    2.69
 1799.68     5.1  1822.3    6.35 1822.67    7.79 1839.08    9.49 1883.92    9.19
 1961.87   12.81 1984.07   11.94 2001.23   15.77 2019.58   18.73 2062.72   21.88
 2079.38   20.88 2097.04   22.11 2194.59   23.38 2526.75   23.08 2727.46   24.16
#Mann= 3 , 0 , 0
       0     .12       0 1767.39     .08       0 1799.68     .12       0
Bank Sta=1767.39,1799.68
XS Rating Curve= 0
Exp/Cntr=.5,.3

Type RM Length L Ch R = 1 ,2164.67 ,157.71,157.1,154.49
BEGIN DESCRIPTION:
XS 3/4.  433s1ufix.
END DESCRIPTION:
XS GIS Cut Line= 6
     3264760.896    13854053.543     3265101.168    13855778.797
      3265112.78    13855824.833      3265121.49    13855857.597
     3265128.126     13855892.02     3265303.518    13856777.899
#Sta/Elev= 30
       0   20.46  802.02   18.64 1167.07   18.69 1278.34   19.75 1639.56    18.3
  1657.6   17.96 1664.95   16.61 1746.33   15.35  1782.6   11.03 1808.48    6.85
 1819.21    -.48 1832.59     .47 1838.16    2.63 1840.77    5.04 1863.39    6.29
 1874.93    9.26 1890.91   11.16 1949.13   11.41 1979.72   13.24 2029.98    14.6
 2056.17   17.27 2070.11   17.64 2092.56   21.71 2251.81   23.39 2341.19   22.15
 2546.16   22.27 2616.44   22.49 2634.23   23.83  2687.1   23.11    2778    23.9
#Mann= 3 , 0 , 0
       0     .12       0 1808.48     .08       0 1840.77     .12       0
#XS Ineff= 2 , 0
       0 1808.48   18.61 1840.77       0   18.61
Permanent Ineff=
       F       F
Bank Sta=1808.48,1840.77
XS Rating Curve= 0
Exp/Cntr=.5,.3

Type RM Length L Ch R = 2 ,2086.12 ,,,
BEGIN DESCRIPTION:
State Highway 146:  433 s1  (concrete double box culverts 10.5'x12')
Stationing on xs 2/4 shifted to the right by 324' to allow for floodway modeling.
END DESCRIPTION:
Bridge Culvert--1,0,-1,-1, 0
Deck Dist Width WeirC Skew NumUp NumDn MinLoCord MaxHiCord MaxSubmerge Is_Ogee
17.045,115.5,2.6,0, 8, 8, 18.61, , .95, 0, 0,0,,
    1500  1639.8 1677.12 1778.21    1824 1881.13 1958.29    2120
   18.61   18.61   20.06    19.8   19.92   20.31   18.93   18.93
      -5      -5      -5      -5      -5      -5      -5      -5
    1544  1634.8 1672.12 1773.21    1819 1876.13 1953.29    2094
   18.61   18.61   20.06    19.8   19.92   20.31   18.93   18.93
      -5      -5      -5      -5      -5      -5      -5      -5
BR Coef=-1 , 0 , 0 ,, 0 ,,,.8,-1,,0,
WSPro=,,,, 1 ,,,, 0 ,,,, 0 ,,,,-1 ,-1 ,-1 , 0 , 0 , 0 , 0 , 0
Multiple Barrel Culv=2,12,10.5,115.5,.012,.5,1,10,1,1.59,1.045, 2,Culvert #1  , 0 ,17.045
 1819.44 1818.44 1830.57 1829.57
Culvert Bottom n=.012
BC Design=,, 0 ,, 0 ,,,,,,

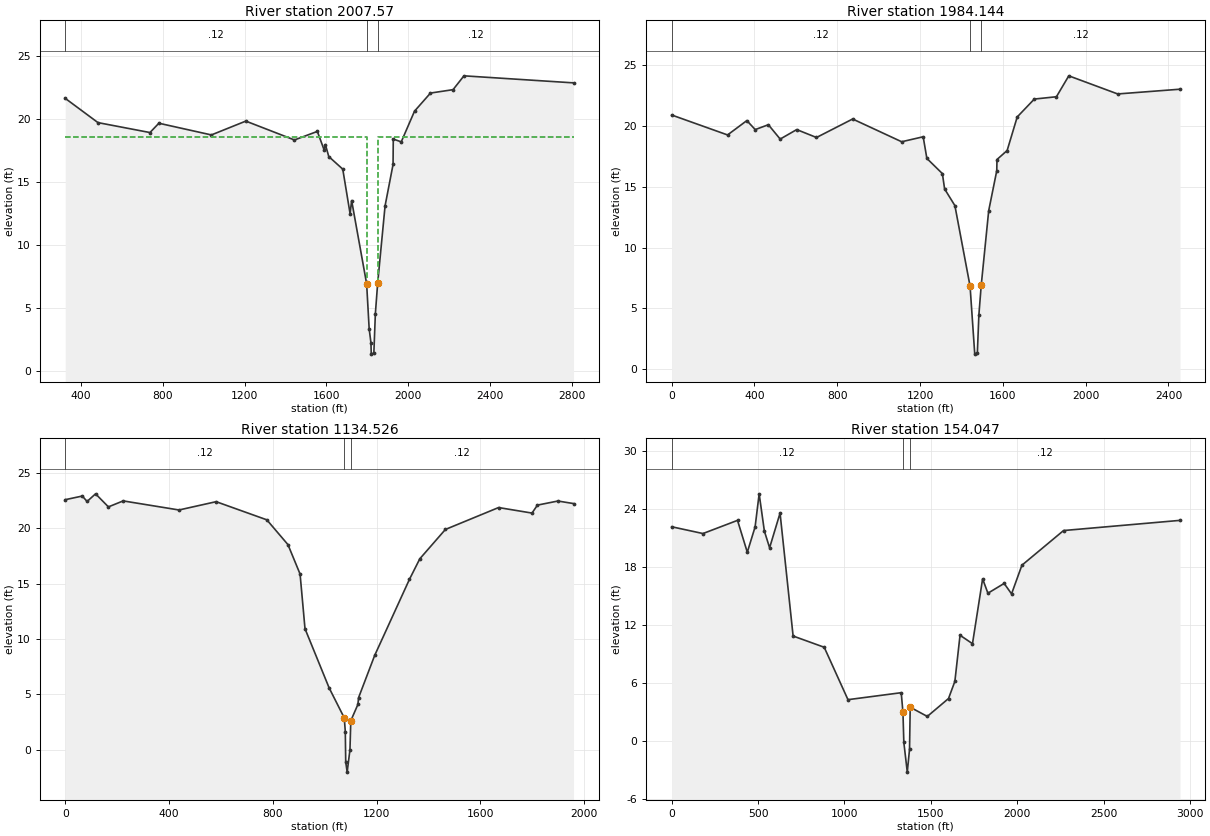
Type RM Length L Ch R = 1 ,2007.57 ,21.72,23.43,23.14
BEGIN DESCRIPTION:
XS 2/4.  Copy of 433s1dfix.  Adjusted elevations based on nearest surveyed sections.
END DESCRIPTION:
XS GIS Cut Line= 4
     3264659.682    13854396.547     3264945.508    13855758.304
     3264994.056    13855943.667      3265157.32    13856828.506
#Sta/Elev= 30
     324   21.67     484   19.74  737.89   18.95   781.5   19.69 1038.05   18.76
 1206.08   19.86 1443.67   18.36 1555.57   19.04 1589.25   17.54 1594.89   17.99
 1611.36   17.04 1679.63   16.04 1715.43    12.5 1723.02   13.54 1796.31    6.92
 1808.58    3.35  1817.2    2.25 1818.97    1.33 1831.54    1.43 1838.94    4.56
  1850.2    6.98 1886.34   13.12 1925.32   16.41 1926.37   18.43 1965.35   18.21
 2030.16   20.65 2108.15   22.09 2218.36   22.36 2271.62   23.46 2806.82    22.9
#Mann= 3 , 0 , 0
     324     .12       0 1796.31     .08       0  1850.2     .12       0
#XS Ineff= 2 , 0
     324 1796.31   18.61  1850.2     324   18.61
Permanent Ineff=
       F       F
Bank Sta=1796.31,1850.2
XS Rating Curve= 0
Exp/Cntr=.5,.3

Type RM Length L Ch R = 1 ,1984.144,856.89,849.62,784.66
BEGIN DESCRIPTION:
XS 1/4.  Copy of 433s1dfix.  Adjusted elevations to match slope between XS 2 and RS 1190.734.  Removed LIDAR pts adjacent to channel based on survey data and photos on d/s side of bridge.
END DESCRIPTION:
XS GIS Cut Line= 5
     3264631.567    13854433.097     3264927.964     13855766.12
     3264945.227    13855842.666     3264960.572    13855905.706
     3265132.016     13856836.94
#Sta/Elev= 30
       0    20.9  269.98   19.26  363.24   20.44  403.57    19.7  467.12    20.1
  524.21   18.92  604.13    19.7  699.67   19.05   874.3   20.57 1111.15    18.7
 1215.09   19.11 1232.87   17.33  1307.9   16.08 1318.57   14.82 1368.27   13.45
 1441.56    6.83 1464.22    1.24 1476.79    1.34 1484.19    4.47 1495.45    6.89
 1531.59   13.03 1570.57   16.32 1571.62   17.24 1620.72   17.98 1669.42   20.74
 1752.05   22.21 1858.82    22.4 1918.55   24.12  2154.8   22.63 2455.81   23.02
#Mann= 3 , 0 , 0
       0     .12       0 1441.56     .08       0 1495.45     .12       0
#Block Obstruct= 1 ,-1
    1250 1368.27   13.45
Bank Sta=1441.56,1495.45
XS Rating Curve= 0
Exp/Cntr=.3,.1

Type RM Length L Ch R = 1 ,1134.526,1010.76,980.48,842.87
BEGIN DESCRIPTION:
433v4
Bank Station offset =      3913
END DESCRIPTION:
XS GIS Cut Line= 6
     3264147.125    13854791.178     3264197.588    13855747.006
      3264170.48    13855868.367     3264122.297    13856021.565
     3264267.125    13856195.888     3264570.294    13856581.644
#Sta/Elev= 30
       0   22.59   65.88   22.92   84.36   22.43  117.03   23.12  166.55   21.94
  223.49   22.48  438.64   21.66  581.77   22.41  777.18   20.77  858.61   18.53
  905.36   15.87  924.33   10.93 1017.39    5.58 1075.74    2.87 1079.66    1.64
  1081.3   -1.11 1086.86   -2.03 1097.69     .01 1100.84    2.61 1128.34    4.09
  1130.7    4.69  1192.8    8.51 1327.08    15.4 1366.91   17.25 1465.48    19.9
 1670.54   21.88 1799.39   21.38 1820.24    22.1  1899.2   22.47 1959.44   22.24
#Mann= 3 , 0 , 0
       0     .12       0 1075.74     .08       0 1100.84     .12       0
Bank Sta=1075.74,1100.84
XS Rating Curve= 0
Exp/Cntr=.3,.1

Type RM Length L Ch R = 1 ,154.047 ,102.91,154.05,82.92
BEGIN DESCRIPTION:
433v5
Bank Station offset =      3636
END DESCRIPTION:
XS GIS Cut Line= 6
     3263394.512    13854527.344     3263294.002    13854909.285
      3263164.72    13855779.688     3263482.538    13856003.553
     3263723.346    13856354.305      3264146.82    13857094.271
#Sta/Elev= 30
       0   22.14  181.04   21.44  381.11    22.8  437.77   19.51  482.96   22.13
  506.36   25.54   536.6   21.69  566.84   19.97  627.33   23.55  702.93   10.86
  882.95     9.7 1020.46    4.29 1328.75    5.01 1338.75    2.97 1343.75    -.11
 1363.75   -3.19 1376.75    -.84 1380.75    3.51 1479.64    2.56  1602.5    4.41
 1639.22    6.18 1669.11   10.94  1741.2   10.07  1799.8   16.76  1830.5   15.28
 1924.49   16.29  1967.3   15.21 2027.23   18.17 2268.36   21.75 2942.31    22.8
#Mann= 3 , 0 , 0
       0     .12       0 1338.75     .08       0 1380.75     .12       0
Bank Sta=1338.75,1380.75
XS Rating Curve= 0
Exp/Cntr=.3,.1

Chan Stop Cuts=-1